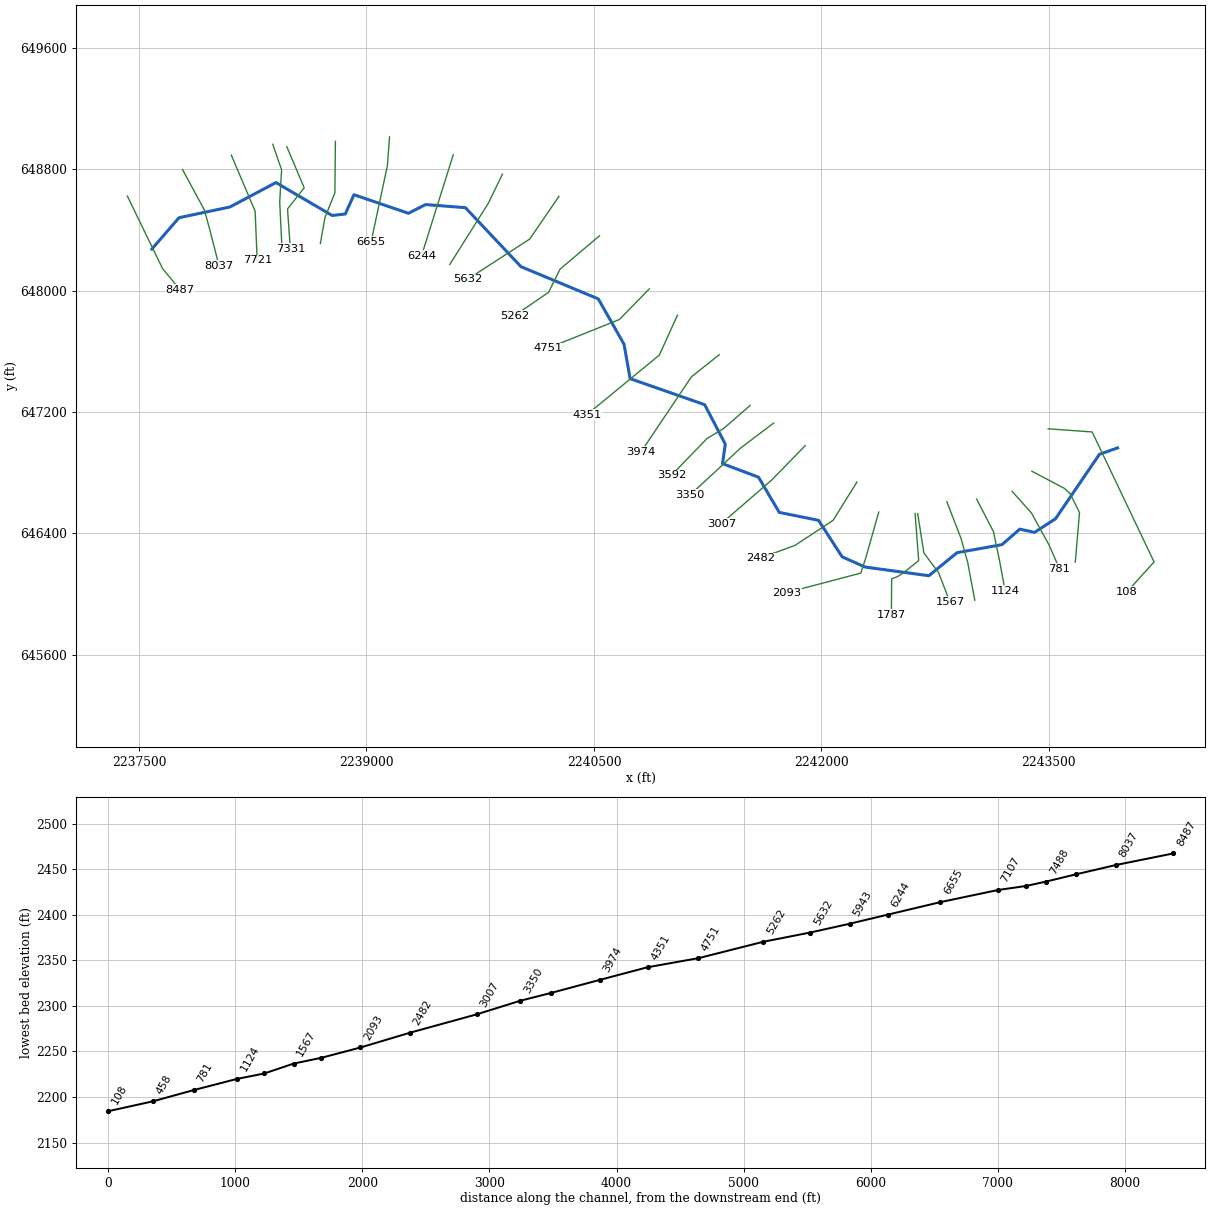
--- LAURELRN1.prj (project) ---

Proj Title=LAURELRN1
Current Plan=p01
Default Exp/Contr=0,0
English Units
Geom File=g01
Flow File=f01
Plan File=p01
BEGIN DESCRIPTION:
----------MODEL BY WSP USA 2022----------
AFH study
Randolph County, WV
HEC-RAS Version: RAS 6.2
Vertical Datum: NAVD88
Projection: NAD 1983 StatePlane West Virginia S FIPS 4702 (US Feet)
Terrain: 1-meter LIDAR (FEMA Region III 3DEP collected 2016-2018)
Land Use: 2019 NLCD
Hydrologic Method:
WV SIR2010-5033 regression equations
Additional Model Notes:
None
END DESCRIPTION:
DSS Export Rating Curves= 0
DSS Export Rating Curve Sorted= 0
DSS Export Volume Flow Curves= 0
DXF OffsetX= 0
DXF OffsetY= 0
DXF ScaleX= 0
DXF ScaleY= 0

--- LAURELRN1.p01 (plan) ---

Plan Title=Floodplain
Program Version=6.20
Short Identifier=Floodplain
Geom File=g01
Flow File=f01
Subcritical Flow
K Sum by GR= 0
Std Step Tol= 0.01
Critical Tol= 0.01
Num of Std Step Trials= 20
Max Error Tol= 0.3
Flow Tol Ratio= 0.001
Split Flow NTrial= 30
Split Flow Tol= 0.02
Split Flow Ratio= 0.02
Log Output Level= 0
Friction Slope Method= 1
Unsteady Friction Slope Method= 2
Unsteady Bridges Friction Slope Method= 1
Parabolic Critical Depth
Global Vel Dist= 0 , 0 , 0
Global Log Level= 0
CheckData=True
Encroach Param=-1 ,0,0, 0
Mapping Interval=1HOUR
Computation Time Step Use Courant=        0
Computation Time Step Use Time Series=    0
Computation Time Step Count To Double=0
Computation Time Step Max Doubling=0
Computation Time Step Max Halving=0
Computation Time Step Residence Courant=0
Run HTab= 0
Run UNet= 0
Run Sediment= 0
Run PostProcess= 0
Run WQNet= 0
Run RASMapper=-1
UNET Theta= 0
UNET Theta Warmup= 0
UNET ZTol= 0
UNET ZSATol= 0
UNET MxIter= 0
UNET Max Iter WO Improvement= 0
UNET MaxInSteps= 0
UNET DtIC= 0
UNET DtMin= 0
UNET MaxCRTS= 0
UNET WFStab= 0
UNET SFStab= 0
UNET WFX= 1
UNET SFX= 1
UNET Gravity=32.174
UNET 1D Methodology=Finite Difference
UNET DSS MLevel= 1
UNET Pardiso=0
UNET DZMax Abort= 0
UNET Use Existing IB Tables= 0
UNET Froude Reduction=False
UNET Froude Limit= 0
UNET Froude Power= 0
UNET D1 Cores= 0
UNET WindReference=Eulerian
UNET WindDragFormulation=Hsu (1988)
UNET D2 Coriolis=0
UNET D2 Cores= 0
UNET D2 Theta= 1
UNET D2 Theta Warmup= 1
UNET D2 Z Tol= 0.01
UNET D2 Volume Tol= 0.01
UNET D2 Max Iterations= 20
UNET D2 Equation= 0
UNET D2 RampUpFraction=0.1
UNET D2 TimeSlices= 1
UNET D2 Turbulence Formulation=Non-Conservative (original)
UNET D2 Eddy Viscosity=0.3
UNET D2 Transverse Eddy Viscosity=0.1
UNET D2 Smagorinsky Mixing=0
UNET D2 BCVolumeCheck=0
UNET D2 Cores=0
UNET D2 SolverType=PARDISO (Direct)
UNET D2 Minimum Iterations= 2147483647
UNET D2 Maximum Iterations= 2147483647
UNET D2 Restart Number= 10
UNET D2 Relaxation Coeff=1.3
UNET D2 SOR Precondition Iterations= 10
UNET D2 ILUT Maximum Fill= 8
UNET D2 ILUT Tolerance=1E-08
UNET D1D2 MaxIter= 0
UNET D1D2 ZTol=0.01
UNET D1D2 QTol=0.1
UNET D1D2 MinQTol=1
Write IC File= 0
Write IC File at Fixed DateTime=0
Write IC File at Sim End=0
Echo Input=False
Echo Parameters=False
Echo Output=False
Write Detailed= 0
HDF Write Warmup=0
HDF Write Time Slices=0
HDF Flush=0
HDF Compression= 1
HDF Chunk Size= 1
HDF Spatial Parts= 1
HDF Use Max Rows=0
HDF Fixed Rows= 1
Calibration Method= 0
Calibration Iterations= 20
Calibration Max Change=0.05
Calibration Tolerance=0.2
Calibration Maximum=1.5
Calibration Minimum=0.5
Calibration Optimization Method= 1
WQ AD Non Conservative
WQ ULTIMATE=-1
WQ Max Comp Step=1HOUR
WQ Output Interval=15MIN
WQ Output Selected Increments= 0
WQ Output face flow=0
WQ Output face velocity=0
WQ Output face area=0
WQ Output face dispersion=0
WQ Output cell volume=0
WQ Output cell surface area=0
WQ Output cell continuity=0
WQ Output cumulative cell continuity=0
WQ Output face conc=0
WQ Output face dconc_dx=0
WQ Output face courant=0
WQ Output face peclet=0
WQ Output face adv mass=0
WQ Output face disp mass=0
WQ Output cell mass=0
WQ Output cell source sink temp=0
WQ Output nsm pathways=0
WQ Output nsm derived pathways=0
WQ Create Restart=0
WQ Fixed Restart=0
WQ System Summary=0
WQ Write To DSS=0
Sorting and Armoring Iterations= 10
XS Update Threshold= 0.02
Bed Roughness Predictor= 0
Hydraulics Update Threshold= 0.02
Energy Slope Method= 1
Volume Change Method= 1
Sediment Retention Method= 0
Sediment TS Multiplier= 1
Warm Up Method= 0
XS Weighting Method= 0
Number of US Weighted Cross Sections= 1
Number of DS Weighted Cross Sections= 1
Upstream XS Weight=0
Main XS Weight=1
Downstream XS Weight=0
Number of DS XS's Weighted with US Boundary= 1
Upstream Boundary Weight= 1
Weight of XSs Associated with US Boundary= 0
Number of US XS's Weighted with DS Boundary= 1
Downstream Boundary Weight= 0.5
Weight of XSs Associated with DS Boundary= 0.5
Percentile Method= 0
Sediment Output Level= 3
Mass or Volume Output= 0
Output Increment Type= 1
Profile and TS Output Increment= 1
Transport Output Increment 1
XS Output Flag= 0
XS Output Increment= 10
Read HDF5 Sediment Hotstart= 0
Sediment Hotstart Type= 0
Write Gradation File= 0
Read Gradation Hotstart= 0
Write HDF5 File= 1
Write Binary Output= 1
Write DSS Sediment File= 0
DSS Sediment Output Type= 1
SV Curve= 0
Specific Gage Flag= 0
Subcell Erosion Methods= 0
Subcell Deposition Methods= 0
Advection Scheme= 1
Matrix Solver= 0
Implicit Weighting Factor= 1
Maximum Outer Loop Convergence Iterations= 5
Convergence Maximum Absolute= 0.001
Convergence RMSE= 0.0001
Grain Fractions Max Abs Error= 0.001
Max Subgrid Regions= 1
Max Subgrid Length Scale= 3.402823E+38
Initial Layer Thickness= 3.402823E+38
Min Layer Thickness= 3.402823E+38
Max Layer Thickness= 3.402823E+38
Number of Layers= 5

--- LAURELRN1.f01 (steady flow) ---

Flow Title=Flow
Program Version=6.20
Number of Profiles= 1
Profile Names=P100yr
River Rch & RM=LAURELRN1,Main,8487
     387
River Rch & RM=LAURELRN1,Main,5262
     446
River Rch & RM=LAURELRN1,Main,2093
     604
Boundary for River Rch & Prof#=LAURELRN1,Main            , 1
Up Type= 0
Dn Type= 3
Dn Slope=0.02976
DSS Import GetInterval= 0
DSS Import GetPeak= 0
DSS Import FillOption= 0

--- LAURELRN1.g01 (geometry) ---

Geom Title=Geometry
Program Version=6.20

River Reach=LAURELRN1       ,Main
Reach XY= 30
2237584.74314386648274.9742240722237763.87700002648481.496000022
2238099.81400003648552.329999998     2238402.939648713.267000005
2238773.77300002648496.0789999962238860.23100002648505.975000009
2238917.52300002      648633.0592239276.89800003648510.663000003
2239389.65800002648568.2150000042239652.41899998648547.642000005
2240018.80800004648158.6790000052240528.79000001647946.005999997
2240698.49500002 647646.961000012240738.63483432 647420.13433373
2241230.17900003647248.523000002  2241366.162809646988.609246034
2241347.80100001646859.6340000032241585.64800002646770.225000009
2241721.93200001646538.0200000112241981.04700002646485.936000019
2242136.86300004646245.0510000142242289.03666627646177.567165688
2242708.68900003646120.5509999992242894.15273578646272.355428442
2243191.16900001 646325.64200002     2243308.002646427.886000007
2243405.97899999646406.481999993     2243543.822646496.246000022
2243833.20714924646921.2036443052243952.98218201 646963.52727963

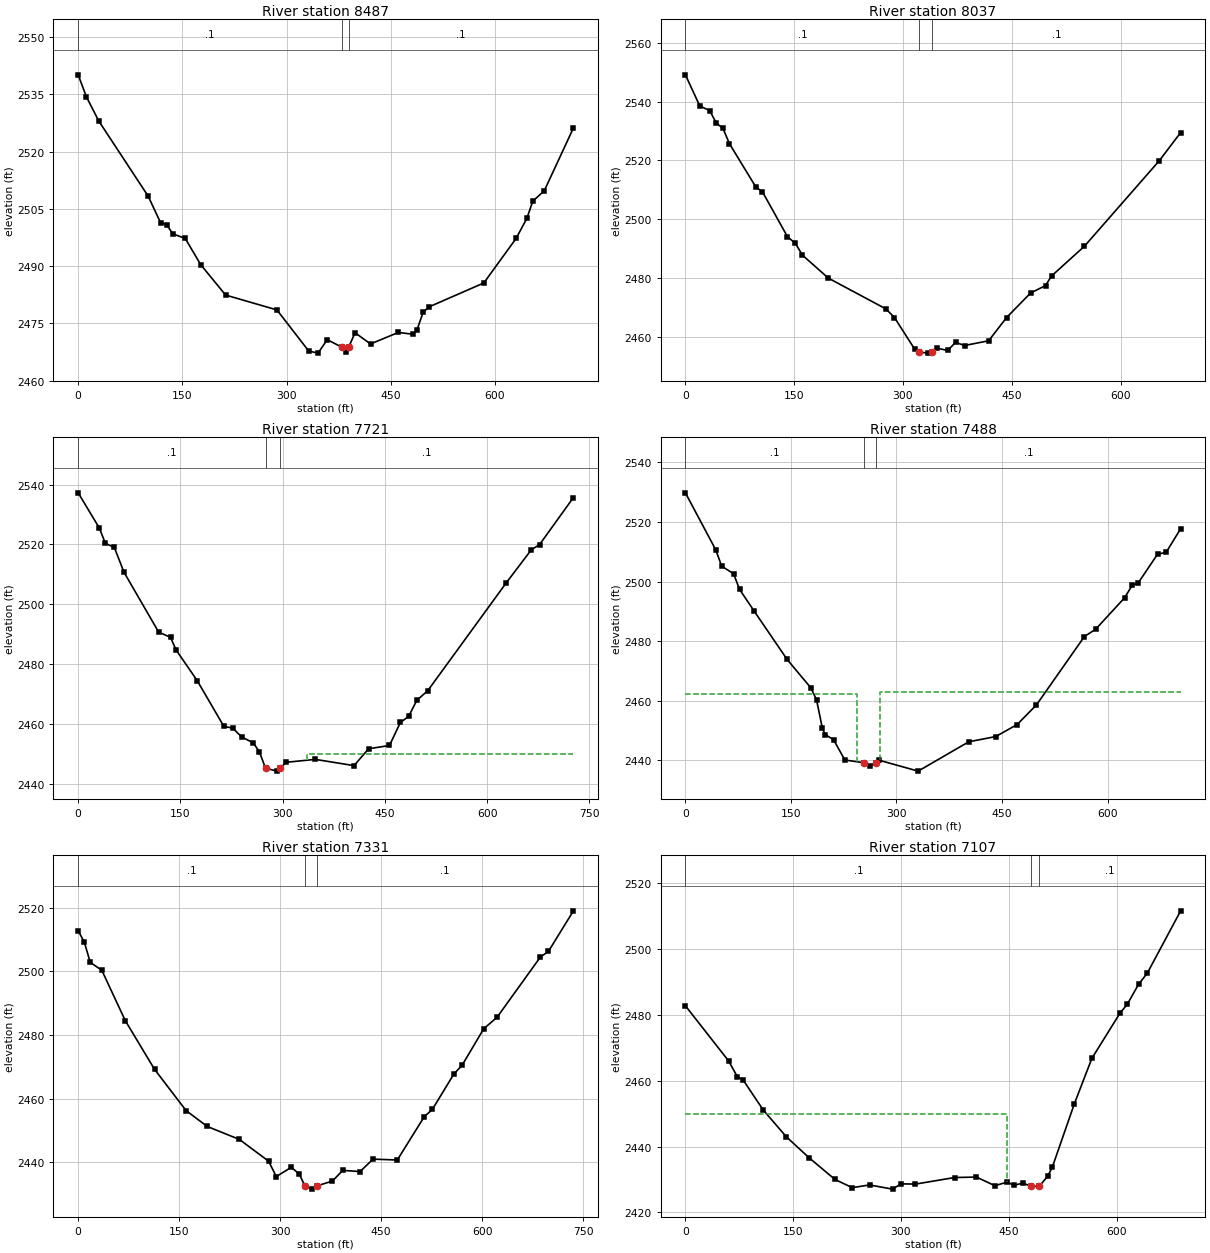
Type RM Length L Ch R = 1 ,8487    ,452.2,450.6,447.4
XS GIS Cut Line= 3
2237423.19531622648623.888967245 2237654.9094219648146.584465765
2237770.80028632648005.492422841
#Sta/Elev= 30
       0 2540.07    11.9 2534.29    29.7 2527.97   100.8 2508.31   118.6 2501.38
   127.5  2500.8   136.4 2498.44   154.2 2497.25   176.4  2490.4   212.3 2482.43
   286.2 2478.54     332 2467.78   345.4 2467.23   358.7 2470.76   379.9 2468.76
   385.4 2467.46  389.46 2468.75   398.7 2472.57     421 2469.63     461 2472.64
   481.7 2472.19   487.7 2473.22   496.8 2477.92   505.6 2479.36   584.2  2485.6
   630.7 2497.26   646.2 2502.53   654.7 2507.01   671.2 2509.72   713.2 2526.17
#Mann= 3 ,0,0
       0      .1       0   379.9    .045       0  389.46      .1       0
Bank Sta=379.9,389.46
XS Rating Curve= 0 ,0
Exp/Cntr(USF)=0,0
Exp/Cntr=0.3,0.1

Type RM Length L Ch R = 1 ,8037    ,313.7,315.5,316
XS GIS Cut Line= 4
2237786.82516252 648798.608593252237930.90850284648532.598306461
2237965.08834695648408.7631136762238027.58893221 648164.74278064
#Sta/Elev= 30
       0 2549.07    19.8 2538.52    33.5 2536.91    42.6 2532.69    51.7 2530.92
    60.8 2525.65    97.2 2510.94   106.3 2509.33   140.7 2494.11   151.7 2491.83
   161.4 2487.83   197.2 2480.02   276.5 2469.57   288.3 2466.65   316.1 2455.91
   322.6  2454.9   335.1 2454.56   339.92454.846   347.6 2456.21   361.6 2455.46
   372.5  2458.2   384.9 2457.15   418.1 2458.75   442.9 2466.65     476 2474.98
   496.6 2477.51   504.9 2480.77   550.3 2490.88   653.5 2519.92   682.9 2529.47
#Mann= 3 ,-1,0
       0      .1       0   322.6    .045       0   339.9      .1       0
Bank Sta=322.6,339.9
XS Rating Curve= 0 ,0
Exp/Cntr(USF)=0,0
Exp/Cntr=0.3,0.1

Type RM Length L Ch R = 1 ,7721    ,237.5,233.8,229.7
XS GIS Cut Line= 3
2238108.77648559648893.9369808682238265.75188938648524.053029714
 2238279.1820818648199.586677732
#Sta/Elev= 30
       0 2537.24    31.2 2525.42    39.9 2520.35      53 2519.02    67.2 2510.73
   118.1 2490.72   135.5 2488.98   143.5 2484.82   174.6 2474.53   213.7 2459.27
   226.8 2458.64   239.8 2455.73   257.2 2453.68   265.9  2450.7   274.9 2445.27
     292  2444.3     296 2445.18     305 2447.25   347.9 2448.22   404.7 2446.14
   426.1 2451.77   456.7 2452.86   472.7 2460.55   484.8 2462.56   496.8 2467.93
   512.8 2471.14   627.8 2507.11   664.9 2518.24   676.9 2519.95   726.6 2535.67
#Mann= 3 ,-1,0
       0      .1       0   274.9    .045       0     296      .1       0
#XS Ineff= 2 , 0
                          335.81         2450.15
Permanent Ineff=
       F       F
Bank Sta=274.9,296
XS Rating Curve= 0 ,0
Exp/Cntr(USF)=0,0
Exp/Cntr=0.3,0.1

Type RM Length L Ch R = 1 ,7488    ,160.9,157.1,150
XS GIS Cut Line= 4
2238381.97533744648965.9268950682238440.21802412 648796.74575757
 2238427.7374484648585.9627010142238442.99148539648272.561577451
#Sta/Elev= 30
       0 2529.78    43.1 2510.67    51.6 2505.16    68.5 2502.63    76.9 2497.41
    98.1 2489.96   144.6 2473.86   178.6 2464.25   186.5  2460.2   194.5 2450.99
   198.5 2448.68   210.5 2446.97   226.6 2440.13  253.64  2439.2   262.6  2438.2
   270.7 2439.19   274.7 2440.09   330.8 2436.39   402.7 2446.23     441 2447.99
   471.4    2452     499 2458.63   567.1 2481.56   583.1 2484.01   624.2 2494.55
   635.2 2498.81   643.2 2499.41   671.2 2509.23   683.2 2509.77   703.9 2517.74
#Mann= 3 ,-1,0
       0      .1       0  253.64    .045       0   270.7      .1       0
#XS Ineff= 2 , 0
          243.35 2462.28   276.1         2462.83
Permanent Ineff=
       F       F
Bank Sta=253.64,270.7
XS Rating Curve= 0 ,0
Exp/Cntr(USF)=0,0
Exp/Cntr=0.3,0.1

Type RM Length L Ch R = 1 ,7331    ,221.5,223.3,225.1
XS GIS Cut Line= 4
2238474.69030357648949.6553614752238589.26436337 648678.70319303
2238479.33519789648539.3563635452238497.91477515648276.145685628
#Sta/Elev= 30
       0 2512.76     9.2 2509.11    17.9 2502.82    35.1 2500.32      70 2484.48
   113.4  2469.2   160.2 2456.24   191.6 2451.25   239.4 2447.17   282.8 2440.33
   294.2  2435.5   316.5 2438.41   328.2 2436.31   336.9 2432.53   347.1 2431.55
  354.572432.567   377.6 2434.09   392.9 2437.44   418.6 2437.07     438 2440.98
   473.9  2440.7     514 2454.32     526  2456.6   558.1 2467.78   570.1 2470.45
   602.2 2481.92   622.2 2485.59   686.4 2504.47   698.4 2506.27   735.5 2519.01
#Mann= 3 ,-1,0
       0      .1       0   336.9    .045       0  354.57      .1       0
Bank Sta=336.9,354.57
XS Rating Curve= 0 ,0
Exp/Cntr(USF)=0,0
Exp/Cntr=0.3,0.1

Type RM Length L Ch R = 1 ,7107    ,451.7,452,452
XS GIS Cut Line= 4
     2238795.022648985.4059890462238791.76224944 648647.17236626
2238725.89007578648481.385018946 2238695.9273061648311.472293074
#Sta/Elev= 30
       0 2482.76    60.2 2465.98    72.2 2461.24    80.2 2460.26   108.2 2451.13
   140.2 2443.01   172.2 2436.57   208.2 2429.99   232.2 2427.51   256.2 2428.33
   288.2 2427.06   300.2 2428.66   320.2 2428.59   374.8 2430.59     405 2430.72
   430.8 2428.09     448 2429.23   456.6 2428.22   469.5 2428.86   481.2 2427.95
   492.5 2427.95     504 2430.93   510.5 2433.66   541.2 2452.94   565.6 2466.76
   604.6 2480.46     615 2483.24   630.6 2489.27   642.8 2492.68   689.2  2511.6
#Mann= 3 ,-1,0
       0      .1       0   481.2    .045       0   492.5      .1       0
#XS Ineff= 2 , 0
          447.29    2450
Permanent Ineff=
       F       F
Bank Sta=481.2,492.5
XS Rating Curve= 0 ,0
Exp/Cntr(USF)=0,0
Exp/Cntr=0.3,0.1

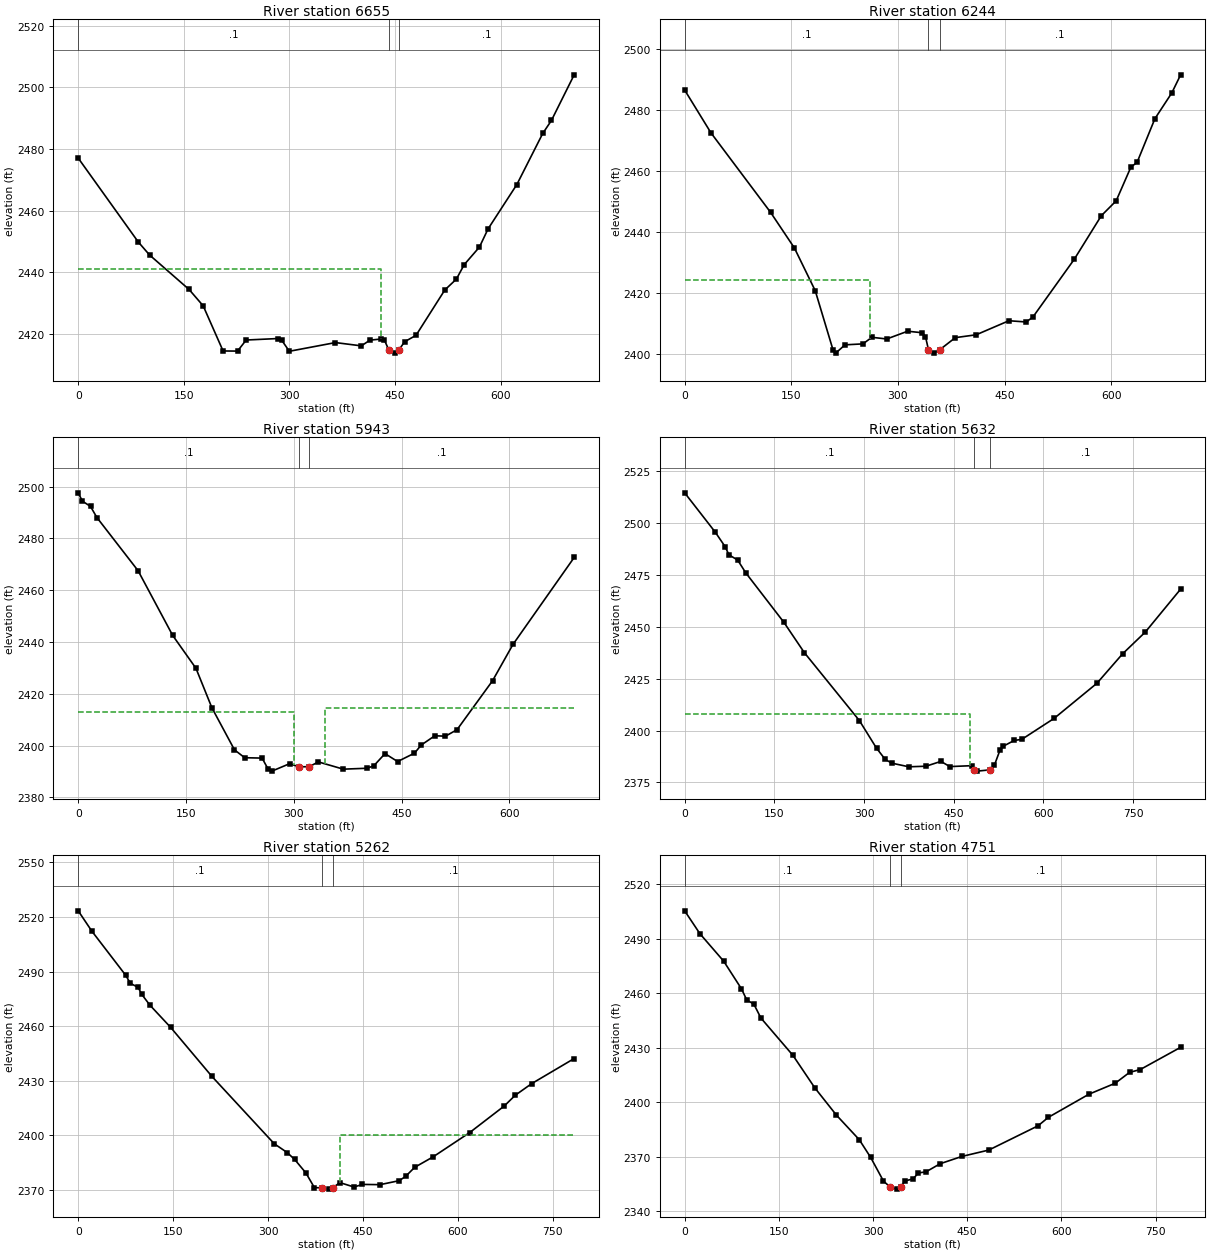
Type RM Length L Ch R = 1 ,6655    ,410.5,411.3,408.7
XS GIS Cut Line= 3
 2239151.9346042649014.1711924212239137.76895115648823.749851393
2239030.29149852648321.531013915
#Sta/Elev= 30
       0 2477.05    85.2 2449.88   101.3 2445.64   157.5 2434.44   177.5 2429.15
   205.8  2414.5   226.3 2414.46   238.6 2418.05   283.6 2418.53   288.8 2418.08
   299.9  2414.4   365.4 2417.22   402.2 2416.16   414.5 2418.02   430.8 2418.38
   434.9 2418.06   441.42414.743   450.5  2413.8   455.4 2414.78   463.6 2417.48
   479.9 2419.58   520.8 2434.29   537.2 2437.81   548.3 2442.49   569.9 2448.18
   582.2 2454.09   623.1 2468.48   659.9 2485.06   672.2 2489.25   704.5 2504.06
#Mann= 3 ,-1,0
       0      .1       0   441.4    .045       0   455.4      .1       0
#XS Ineff= 2 , 0
          429.75 2440.97
Permanent Ineff=
       F       F
Bank Sta=441.4,455.4
XS Rating Curve= 0 ,0
Exp/Cntr(USF)=0,0
Exp/Cntr=0.3,0.1

Type RM Length L Ch R = 1 ,6244    ,302.8,301.1,299.3
XS GIS Cut Line= 2
2239572.10449455648896.4483612282239363.08425033648230.680175909
#Sta/Elev= 30
       0 2486.43      37 2472.38   120.8 2446.34   154.4 2434.63   183.7 2420.62
   208.9 2401.07   213.1 2400.28   225.6 2402.87   250.8 2403.18   263.4 2405.34
   284.3 2404.79   313.7 2407.33   334.6 2406.83   338.8 2405.57     343 2401.28
   350.3 2400.15  358.792401.245   380.8 2405.23   410.1 2406.16   456.2 2410.77
   480.5 2410.37   489.8 2411.93   548.2 2430.95   586.2 2445.21   607.1 2450.09
   627.9 2461.19   636.5 2462.68   661.6 2477.03   685.4 2485.49   697.8 2491.42
#Mann= 3 ,-1,0
       0      .1       0     343    .045       0  358.79      .1       0
#XS Ineff= 2 , 0
          260.29 2424.14
Permanent Ineff=
       F       F
Bank Sta=343,358.79
XS Rating Curve= 0 ,0
Exp/Cntr(USF)=0,0
Exp/Cntr=0.3,0.1

Type RM Length L Ch R = 1 ,5943    ,314.3,311.3,307.4
XS GIS Cut Line= 3
2239896.59149053648768.5558913552239803.81391622648577.634962108
2239549.41181853648173.054271167
#Sta/Elev= 30
       0 2497.59     5.8 2494.39    17.1 2492.34      26 2488.05    83.3 2467.52
   131.5 2442.52   163.9 2429.81   186.1 2414.55   217.5 2398.33   231.7  2395.3
   255.9 2395.15   264.6 2390.75   269.5 2390.12   294.2 2392.99   307.3 2391.78
   321.5 2391.84   334.2 2393.68     369 2390.88   401.8 2391.23   411.3 2392.16
     427 2396.88   444.5 2393.82     468 2397.06   477.4  2400.2   496.3 2403.78
   511.1 2403.61   527.2 2406.12   576.6 2425.01     605 2439.02   690.2 2472.62
#Mann= 3 ,-1,0
       0      .1       0   307.3    .045       0   321.5      .1       0
#XS Ineff= 2 , 0
          300.12 2412.94  343.18         2414.34
Permanent Ineff=
       F       F
Bank Sta=307.3,321.5
XS Rating Curve= 0 ,0
Exp/Cntr(USF)=0,0
Exp/Cntr=0.3,0.1

Type RM Length L Ch R = 1 ,5632    ,362.4,369.8,376.9
XS GIS Cut Line= 3
2240269.16880758 648622.29175074 2240076.5443958648340.750320013
2239666.66543369648075.283146537
#Sta/Elev= 30
       0  2514.6    51.3 2495.58    67.7 2488.63      74 2484.72    88.6  2482.2
   102.2 2476.02   166.1 2452.11   200.1 2437.58   292.2 2404.81   320.9 2391.49
   335.3 2386.13   346.3 2384.29   374.9 2382.53   403.5  2382.8   428.6 2385.14
   443.4 2382.63   479.8 2383.06   484.5 2381.13   489.3 2380.44   511.22381.073
   517.9 2383.21   527.4 2390.57     532 2392.32   551.3 2395.25   563.8 2395.74
     618 2405.88   689.5 2422.79   732.4 2436.97   770.5  2447.5   829.5 2468.17
#Mann= 3 ,-1,0
       0      .1       0   484.5    .045       0   511.2      .1       0
#XS Ineff= 2 , 0
          476.53 2407.76
Permanent Ineff=
       F       F
Bank Sta=484.5,511.2
XS Rating Curve= 0 ,0
Exp/Cntr(USF)=0,0
Exp/Cntr=0.3,0.1

Type RM Length L Ch R = 1 ,5262    ,514.9,510.3,502.1
XS GIS Cut Line= 4
2240536.69421422648362.2855148672240276.58013251648142.427183901
2240200.71352535647989.1456714672239976.21030006647835.864159033
#Sta/Elev= 30
       0 2523.39    21.6 2512.18      75 2487.94    82.3 2483.54    94.7 2481.25
   100.5 2477.39   113.2 2471.52   145.9 2459.32   211.2  2432.3   309.7 2395.24
   330.1 2390.42     342 2386.59   359.8 2379.14   373.2 2371.06  385.432371.048
   395.5 2370.28  402.552371.143   413.4 2373.86   435.7 2371.45   449.1 2372.87
   476.8 2372.74   507.1 2374.93   517.1 2377.26   531.6 2382.28   560.7 2388.04
   618.5  2401.4   673.2 2416.05   690.4 2421.91   716.3  2428.3   783.5 2442.12
#Mann= 3 ,-1,0
       0      .1       0  385.43    .045       0  402.55      .1       0
#XS Ineff= 2 , 0
                          414.15         2400.03
Permanent Ineff=
       F       F
Bank Sta=385.43,402.55
XS Rating Curve= 0 ,0
Exp/Cntr(USF)=0,0
Exp/Cntr=0.3,0.1

Type RM Length L Ch R = 1 ,4751    ,398.2,400.2,401.7
XS GIS Cut Line= 3
 2240865.1570897648011.9732433382240668.23859118 647810.52471788
2240196.77817348647621.221981054
#Sta/Elev= 30
       0 2505.43    24.3 2492.82    62.1 2477.73    90.4 2462.53    98.8 2456.42
   110.2 2454.06   121.4 2446.43   172.4 2425.89   207.4 2407.94   241.7 2392.98
     278  2379.5   296.1 2369.78   316.6  2356.7   326.82353.558   337.8 2352.28
   344.2 2353.58   350.7 2356.76   363.7 2357.92   372.3 2361.19   384.3 2361.79
   406.8 2366.25   441.3 2370.26   484.4 2373.79   562.7 2387.12   579.2  2391.8
   643.8 2404.52   685.7 2410.56   708.5 2416.54   725.5 2418.08   789.8 2430.32
#Mann= 3 ,-1,0
       0      .1       0   326.8    .045       0   344.2      .1       0
Bank Sta=326.8,344.2
XS Rating Curve= 0 ,0
Exp/Cntr(USF)=0,0
Exp/Cntr=0.3,0.1

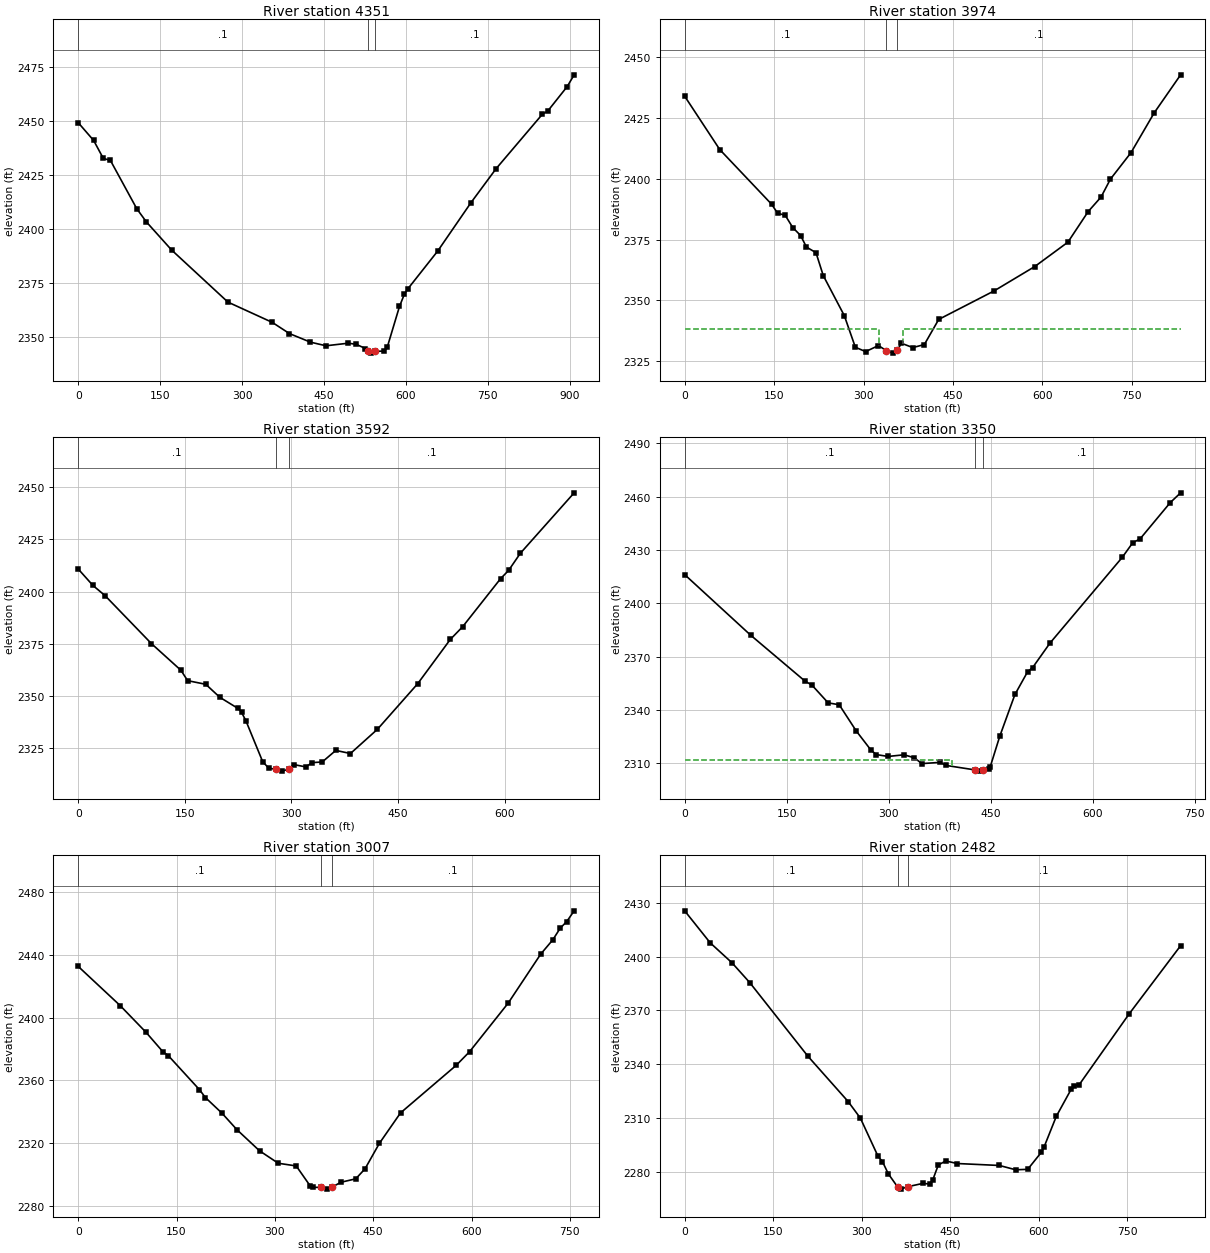
Type RM Length L Ch R = 1 ,4351    ,375.5,377.4,376.2
XS GIS Cut Line= 3
2241050.72918521647838.9607552442240931.51023109647575.750077327
2240453.08611652647182.482358557
#Sta/Elev= 30
       0  2449.2    28.3 2440.94    45.9 2432.65      59 2431.68   107.3 2409.27
   124.9 2403.16     171 2390.16   274.2 2365.99   355.4 2356.59   386.9 2351.39
   425.3 2347.42   453.8 2345.74   494.9 2346.94   509.1 2346.41   526.1 2344.47
  530.192343.154   536.6 2342.33   543.2 2343.21   560.3 2343.24     566 2345.07
   588.4 2363.97   597.2 2369.56   603.9  2372.2   658.4 2389.66   719.4 2412.13
   765.4 2427.88   850.2 2453.14   859.9 2454.57   895.6 2465.95   908.3 2471.38
#Mann= 3 ,-1,0
       0      .1       0  530.19    .045       0   543.2      .1       0
Bank Sta=530.19,543.2
XS Rating Curve= 0 ,0
Exp/Cntr(USF)=0,0
Exp/Cntr=0.3,0.1

Type RM Length L Ch R = 1 ,3974    ,385.3,382.1,377.1
XS GIS Cut Line= 3
 2241326.2274257647578.0052462992241143.00493517647432.652924216
2240809.81098105646936.314558319
#Sta/Elev= 30
       0 2433.82    58.8 2411.93   145.6 2389.53   155.8 2385.84   168.7  2384.9
   181.3  2379.9   194.4 2376.65   204.2 2371.91   220.2  2369.6   232.4  2360.2
   267.7 2343.77   286.2  2330.8   303.5    2329   324.9 2331.49  337.892329.452
   348.9 2328.38   356.6 2329.46   363.3 2332.45   382.5 2330.66   401.9 2331.89
     426 2342.21   518.8  2353.9   587.2 2363.93   642.7 2373.92   676.7 2386.48
   698.3 2392.45     714 2399.79   748.6 2410.69   787.3 2426.95   831.7 2442.59
#Mann= 3 ,-1,0
       0      .1       0  337.89    .045       0   356.6      .1       0
#XS Ineff= 2 , 0
          325.44 2338.22  365.29         2338.39
Permanent Ineff=
       F       F
Bank Sta=337.89,356.6
XS Rating Curve= 0 ,0
Exp/Cntr(USF)=0,0
Exp/Cntr=0.3,0.1

Type RM Length L Ch R = 1 ,3592    ,243.5,241.3,241.9
XS GIS Cut Line= 4
2241530.58764415647244.0404868612241354.98968799647091.188379939
2241245.80961161647025.6803341152241011.07244741646782.754664184
#Sta/Elev= 30
       0 2410.77    20.7 2402.91    37.8 2398.03     103 2375.11   144.5 2362.36
     154 2357.38   179.5 2355.64   199.3 2349.42   224.9 2344.09   229.8 2342.29
   236.1  2338.1   259.6 2318.63   268.4 2315.44   278.1  2315.1   287.4 2314.12
   296.7 2315.18   303.4 2317.24   320.1 2316.16   329.4 2318.19   343.4  2318.5
   362.5 2324.03   383.1 2322.54     421 2334.11   477.6 2355.87   523.7 2377.13
   540.9 2383.14   594.4 2406.17   605.6 2410.07   622.3 2418.34   697.9  2447.2
#Mann= 3 ,-1,0
       0      .1       0   278.1    .045       0   296.7      .1       0
Bank Sta=278.1,296.7
XS Rating Curve= 0 ,0
Exp/Cntr(USF)=0,0
Exp/Cntr=0.3,0.1

Type RM Length L Ch R = 1 ,3350    ,345,343.8,341
XS GIS Cut Line= 4
2241685.41410626647127.4670784662241465.28891695646961.098720694
2241311.84972841646817.5301178242241133.02426405  646652.7883016
#Sta/Elev= 30
       0 2416.13    96.8 2382.13   176.7 2356.28   187.1 2353.98     211 2343.97
   227.2 2342.93   252.2 2328.21   273.8 2317.46   281.7 2314.88   299.2 2313.84
   322.6 2314.77   337.7 2313.08   348.7 2309.81   375.7 2310.51   384.2 2308.79
   427.42306.233   432.3 2305.58     438 2306.22   447.3 2306.81   449.3 2308.07
   463.4 2325.32   485.6  2348.7   504.3 2361.54   511.6 2363.83     537 2377.55
   643.3  2425.8   658.8 2434.05   669.6 2436.23     714 2456.66   729.2 2462.14
#Mann= 3 ,-1,0
       0      .1       0   427.4    .045       0     438      .1       0
#XS Ineff= 2 , 0
          392.75 2311.88
Permanent Ineff=
       F       F
Bank Sta=427.4,438
XS Rating Curve= 0 ,0
Exp/Cntr(USF)=0,0
Exp/Cntr=0.3,0.1

Type RM Length L Ch R = 1 ,3007    ,524.7,524.8,521.7
XS GIS Cut Line= 3
 2241893.3986042646978.3517208412241672.13443369646751.703173476
2241339.59685642646463.844550326
#Sta/Elev= 30
       0 2432.76    63.9  2407.8   103.5 2390.68     129 2378.38   137.5 2375.78
     185 2354.06     194 2349.08   219.5    2339   242.1 2328.56   276.6 2315.07
   305.2 2307.11   332.6  2305.4   353.7 2292.78   358.2 2291.76   370.3 2291.69
   380.2  2290.6   386.6 2291.74   400.7 2294.97   423.4 2297.18   437.6 2303.59
   459.5 2319.85   491.7 2339.24   576.6  2369.6   597.1 2378.34     656 2409.36
   705.6 2440.62     724 2449.72   735.4 2457.21   745.2 2461.35   756.6 2468.24
#Mann= 3 ,-1,0
       0      .1       0   370.3    .045       0   386.6      .1       0
Bank Sta=370.3,386.6
XS Rating Curve= 0 ,0
Exp/Cntr(USF)=0,0
Exp/Cntr=0.3,0.1

Type RM Length L Ch R = 1 ,2482    ,381.1,388.6,393.9
XS GIS Cut Line= 4
2242234.48982652646738.5979212552242077.25082908646485.748211129
2241827.20569893 646321.518593252241598.65462315646236.893493488
#Sta/Elev= 30
       0 2425.53    43.4 2407.65    80.1 2396.61   110.2 2385.58   208.9  2344.5
   277.1 2319.25   297.8 2310.03   327.8  2288.7   335.2 2285.81   345.2 2278.96
  360.732271.764     366 2270.46   378.32271.826   404.3 2273.69   415.4 2273.26
   420.3 2275.42   429.9 2283.92   442.6 2286.16   461.8 2284.73   533.5 2283.64
   561.1 2281.23   581.4 2281.49   604.4 2290.92   608.9 2293.73     630 2311.09
   655.6 2326.41   659.9 2328.11   668.4  2328.5   753.7 2368.26   840.6  2406.1
#Mann= 3 ,-1,0
       0      .1       0  360.73    .045       0   378.3      .1       0
Bank Sta=360.73,378.3
XS Rating Curve= 0 ,0
Exp/Cntr(USF)=0,0
Exp/Cntr=0.3,0.1

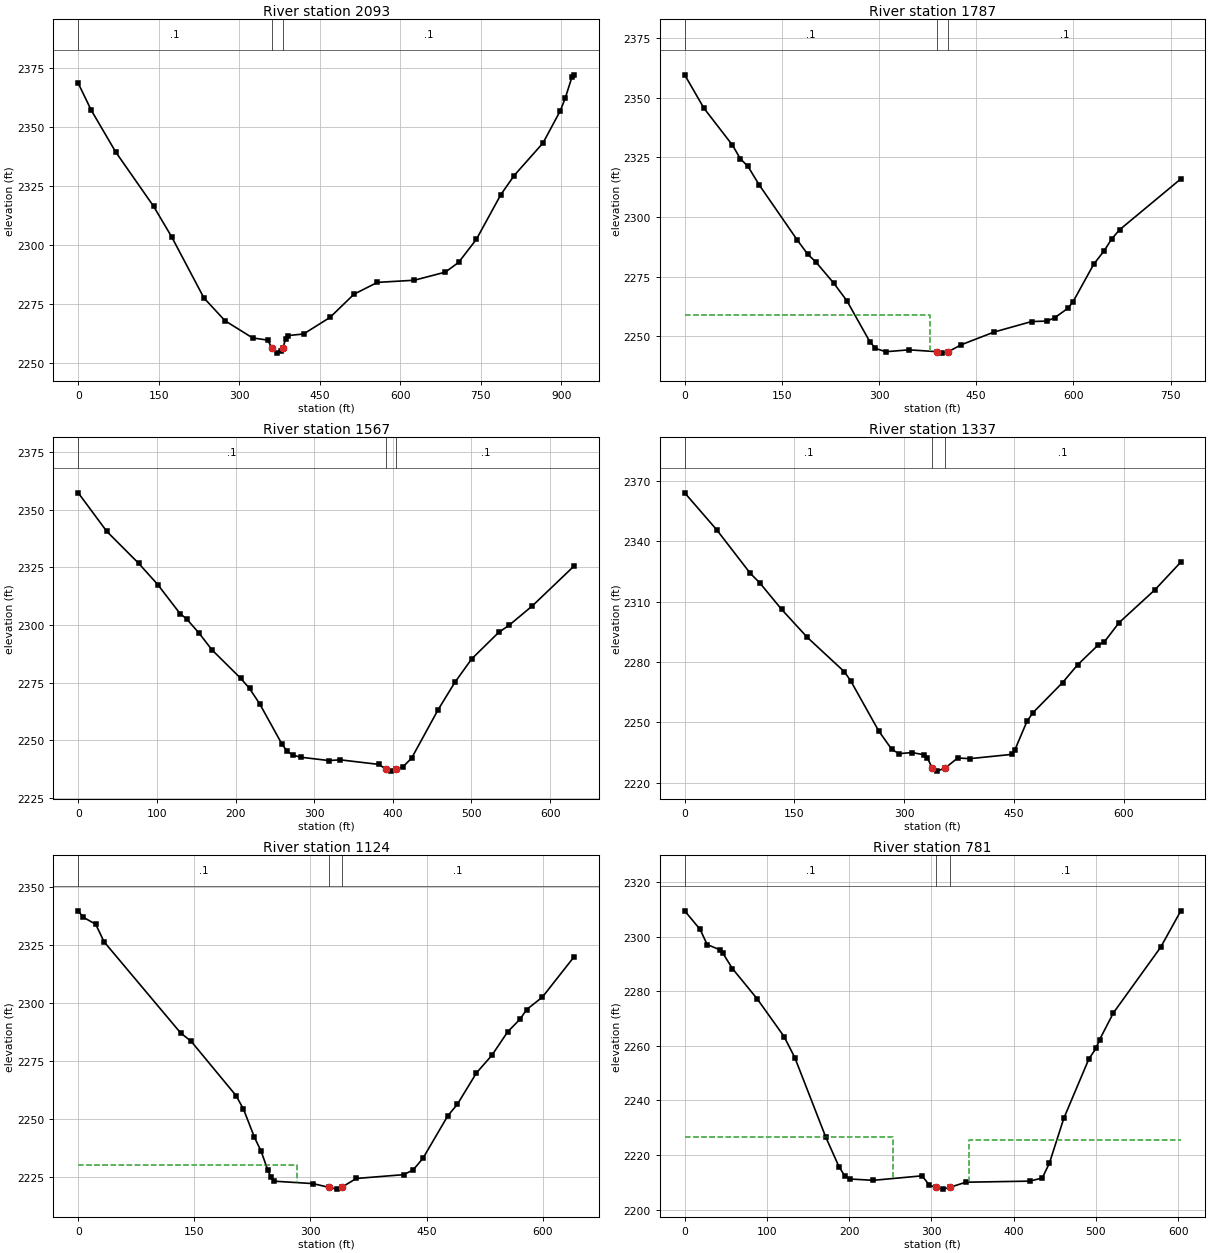
Type RM Length L Ch R = 1 ,2093    ,307.7,306.7,300.5
XS GIS Cut Line= 4
2242378.16618277646540.4624646462242291.50028181646234.159077531
2242259.72137771646137.7501274332241772.00747451646009.551044306
#Sta/Elev= 30
       0 2368.46    24.2 2357.07    69.9 2339.35   140.4  2316.4   173.9 2303.56
   234.3  2277.6   273.6 2267.96   324.9 2260.71   353.1 2259.77   361.5 2256.29
   369.9 2254.27   378.3 2255.02  380.962256.301   386.7 2260.33     391 2261.69
   419.9 2262.37   469.1 2269.36   513.8 2279.19   557.5  2284.2   626.3 2285.11
   684.1 2288.54   708.9 2292.68     742 2302.45   787.5 2321.32   812.3 2329.41
     866 2343.15   898.1 2356.73   907.4 2362.06   919.8 2370.96   924.1 2372.01
#Mann= 3 ,-1,0
       0      .1       0   361.5    .045       0  380.96      .1       0
Bank Sta=361.5,380.96
XS Rating Curve= 0 ,0
Exp/Cntr(USF)=0,0
Exp/Cntr=0.3,0.1

Type RM Length L Ch R = 1 ,1787    ,207.5,219.6,228.9
BEGIN DESCRIPTION:
Dirt road
END DESCRIPTION:
XS GIS Cut Line= 6
2242617.84272948646530.708186582 2242641.5316905646219.964756829
2242538.41503668646137.7501274332242500.79139272 646114.06116642
2242463.16774875646100.1264834712242461.52843715645863.045068204
#Sta/Elev= 30
       0 2359.54    29.6 2345.62    73.8 2330.07    85.8 2324.44    97.8 2321.15
     115 2313.44   174.1 2290.23   190.1 2284.33   202.2 2281.25   230.3 2272.21
   250.3 2264.93   285.7 2247.81   294.5 2244.95   310.5 2243.56   346.2 2244.36
388.94882243.597   397.4 2242.98407.18882243.617   426.8 2246.48   477.8 2251.83
   535.4  2256.2   559.4 2256.41   571.4 2257.85   591.4 2261.74   599.4 2264.47
   631.4 2280.22   647.4 2285.83   659.4  2290.9   671.4 2294.67   765.5 2315.88
#Mann= 3 ,-1,0
       0      .1       0388.9488    .045       0407.1888      .1       0
#XS Ineff= 2 , 0
          379.06 2259.03
Permanent Ineff=
       F       F
Bank Sta=388.9488,407.1888
XS Rating Curve= 0 ,0
Exp/Cntr(USF)=0,0
Exp/Cntr=0.3,0.1

Type RM Length L Ch R = 1 ,1567    ,232.3,230.2,225.7
XS GIS Cut Line= 4
2242635.14674832646529.0640969782242675.58381364646271.277805541
2242772.63277042646140.8682698732242847.44134127645947.781282954
#Sta/Elev= 30
       0 2357.28    36.3 2340.57    76.8 2326.73   101.1  2317.5   129.4 2304.94
   137.9 2302.57   153.7 2296.43   169.9 2289.24   206.4 2276.91   217.8 2272.45
   230.7  2265.8     259 2248.34   265.7 2245.18   273.5 2243.47   283.5  2242.6
   318.4 2241.19   333.4 2241.48   382.5 2239.49   391.5 2237.33   397.2 2236.59
   404.7 2237.37   413.1 2238.55   423.8 2242.14   457.5 2263.15   478.9 2275.08
   500.4 2285.28   534.7 2296.77   547.6 2299.77   577.6  2308.3   630.6 2325.57
#Mann= 3 ,-1,0
       0      .1       0   391.5    .045       0   404.7      .1       0
Bank Sta=391.5,404.7
XS Rating Curve= 0 ,0
Exp/Cntr(USF)=0,0
Exp/Cntr=0.3,0.1

Type RM Length L Ch R = 1 ,1337    ,213.6,213.1,212.4
XS GIS Cut Line= 4
2242827.22129295646608.8547211662242920.69727105646366.544829811
2242965.35462234646205.6610838632243011.65540367645958.661214654
#Sta/Elev= 30
       0 2364.14    43.8 2345.74    89.7  2324.1   102.5 2319.41   132.6 2306.14
   167.6 2292.27   218.3 2275.16   226.9 2270.68   265.3  2245.7   283.1 2236.56
   292.9 2234.43   310.9 2234.98   327.6 2233.84   331.7 2232.36   338.4  2227.3
   344.9 2225.74   356.2 2227.28   373.2 2232.28   389.8 2231.94   447.5 2234.08
   451.6 2236.45   467.9 2250.48     476 2254.75   516.7 2269.81   537.1 2278.56
   565.5 2288.54   573.5 2289.91     594 2299.63   642.9 2315.92     678 2329.58
#Mann= 3 ,-1,0
       0      .1       0   338.4    .045       0   356.2      .1       0
Bank Sta=338.4,356.2
XS Rating Curve= 0 ,0
Exp/Cntr(USF)=0,0
Exp/Cntr=0.3,0.1

Type RM Length L Ch R = 1 ,1124    ,339.6,343.2,344.4
XS GIS Cut Line= 4
2243023.34200329646626.8574989272243134.81946687646410.869913224
2243175.23004743646217.1778202392243211.46022309646020.698790665
#Sta/Elev= 30
       0 2339.91     6.4 2337.15    22.6 2334.12    33.4 2326.55   132.4  2287.2
   145.9 2283.63   203.8 2260.24   213.5 2254.37   227.5 2242.36   236.4  2236.1
   244.8 2228.17     249 2224.92     253 2223.29   303.1 2222.25  323.572220.655
   334.7 2219.86   340.3 2220.63   359.2 2224.46   420.5  2226.1   432.7 2228.15
   445.2 2233.08   477.5 2251.49   489.8 2256.45   514.5    2270   534.5 2277.62
   554.8 2287.71   571.1 2293.28   579.2 2297.29   599.6 2302.67   640.7 2320.12
#Mann= 3 ,-1,0
       0      .1       0  323.57    .045       0   340.3      .1       0
#XS Ineff= 2 , 0
          282.13 2230.16
Permanent Ineff=
       F       F
Bank Sta=323.57,340.3
XS Rating Curve= 0 ,0
Exp/Cntr(USF)=0,0
Exp/Cntr=0.3,0.1

Type RM Length L Ch R = 1 ,781     ,320.5,322.3,325.1
XS GIS Cut Line= 4
2243257.44467682646677.0223575422243385.64375995646533.495123172
2243502.69509672646320.2944740592243569.58157487646167.012961625
#Sta/Elev= 30
       0 2309.53    18.8 2302.69    27.3 2297.18    42.7 2295.25    46.1 2294.14
    58.1 2288.34    88.2 2277.23   120.8 2263.45   133.9  2255.7   171.4 2226.65
   187.5 2215.77   194.5 2212.37   200.4 2211.21   229.3 2210.72   288.6 2212.37
   297.6 2208.89   305.8 2208.13   314.1 2207.49   322.4 2208.14   341.8 2210.03
   419.6 2210.42   434.7 2211.57   443.4 2217.02   460.9 2233.46   491.4 2255.25
   500.2 2259.16   504.5 2262.35   521.2 2272.12   578.7  2296.2   602.9 2309.39
#Mann= 3 ,-1,0
       0      .1       0   305.8    .045       0   322.4      .1       0
#XS Ineff= 2 , 0
          253.21 2226.48  345.15         2225.54
Permanent Ineff=
       F       F
Bank Sta=305.8,322.4
XS Rating Curve= 0 ,0
Exp/Cntr(USF)=0,0
Exp/Cntr=0.3,0.1

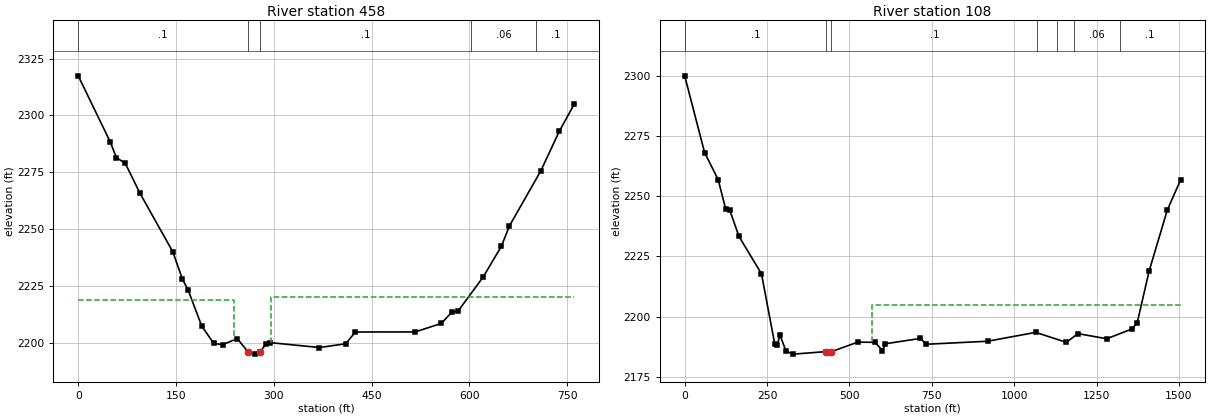
Type RM Length L Ch R = 1 ,458     ,352.5,350.6,347
XS GIS Cut Line= 5
2243388.43069654646809.4018455532243604.18602651646695.647859093
2243640.42371745646661.4400247722243702.02556426646536.956688171
2243674.35895707646210.295270045
#Sta/Elev= 30
       0 2317.41    49.5 2288.15    58.5 2281.46    72.1 2278.99    94.7  2265.8
   145.1 2240.06   159.9 2228.01   168.7 2223.18   189.5  2207.4   207.7 2199.89
   221.3 2199.25   243.9 2201.97   260.2 2196.15   270.8 2195.12  279.31 2196.16
   287.9 2199.67     294 2200.18   369.9 2198.03   410.1 2199.67   425.1 2204.85
   516.7 2204.87   556.9 2208.62   572.9 2213.59   582.2 2213.92   621.1 2229.06
   648.8 2242.43   661.2 2251.42   709.4 2275.66   737.6 2292.98   760.5  2304.9
#Mann= 5 ,-1,0
       0      .1       0   260.2    .045       0  279.31      .1       0
  602.63     .06       0  702.63      .1       0
#XS Ineff= 2 , 0
          238.99  2219.1  295.42         2220.03
Permanent Ineff=
       F       F
Bank Sta=260.2,279.31
XS Rating Curve= 0 ,0
Exp/Cntr(USF)=0,0
Exp/Cntr=0.3,0.1

Type RM Length L Ch R = 1 ,108     ,,,
XS GIS Cut Line= 4
2243495.72775524647089.4889728192243785.56916057647068.586948396
2244193.85537096 646211.603947062244015.49142922646015.124917485
#Sta/Elev= 30
       0 2300.23    60.6  2268.2   101.7 2256.98   124.8 2244.58   136.8 2244.28
   164.9 2233.33   233.1 2217.77   273.2 2188.66   281.2 2188.19   289.2 2192.32
   307.7  2185.5   329.8 2184.33   430.2 2185.39   445.5 2185.36   524.8 2189.31
   577.9 2189.26   600.1 2185.81     609 2188.64   715.2 2190.87   733.3 2188.45
   919.1 2189.69  1065.3 2193.39  1158.4 2189.24  1193.8 2192.87    1281 2190.73
  1356.6 2194.76  1373.3 2197.32  1409.8 2219.03  1464.6 2244.27  1505.2 2256.91
#Mann= 7 ,-1,0
       0      .1       0   430.2    .045       0   445.5      .1       0
 1070.59     .06       0 1130.59      .1       0 1180.59     .06       0
 1319.87      .1       0
#XS Ineff= 2 , 0
                          569.53         2204.62
Permanent Ineff=
       F       F
Bank Sta=430.2,445.5
XS Rating Curve= 0 ,0
Exp/Cntr(USF)=0,0
Exp/Cntr=0.3,0.1
LCMann Table=0

Chan Stop Cuts=-1
Use User Specified Reach Order=0
Composite Channel Slope=5